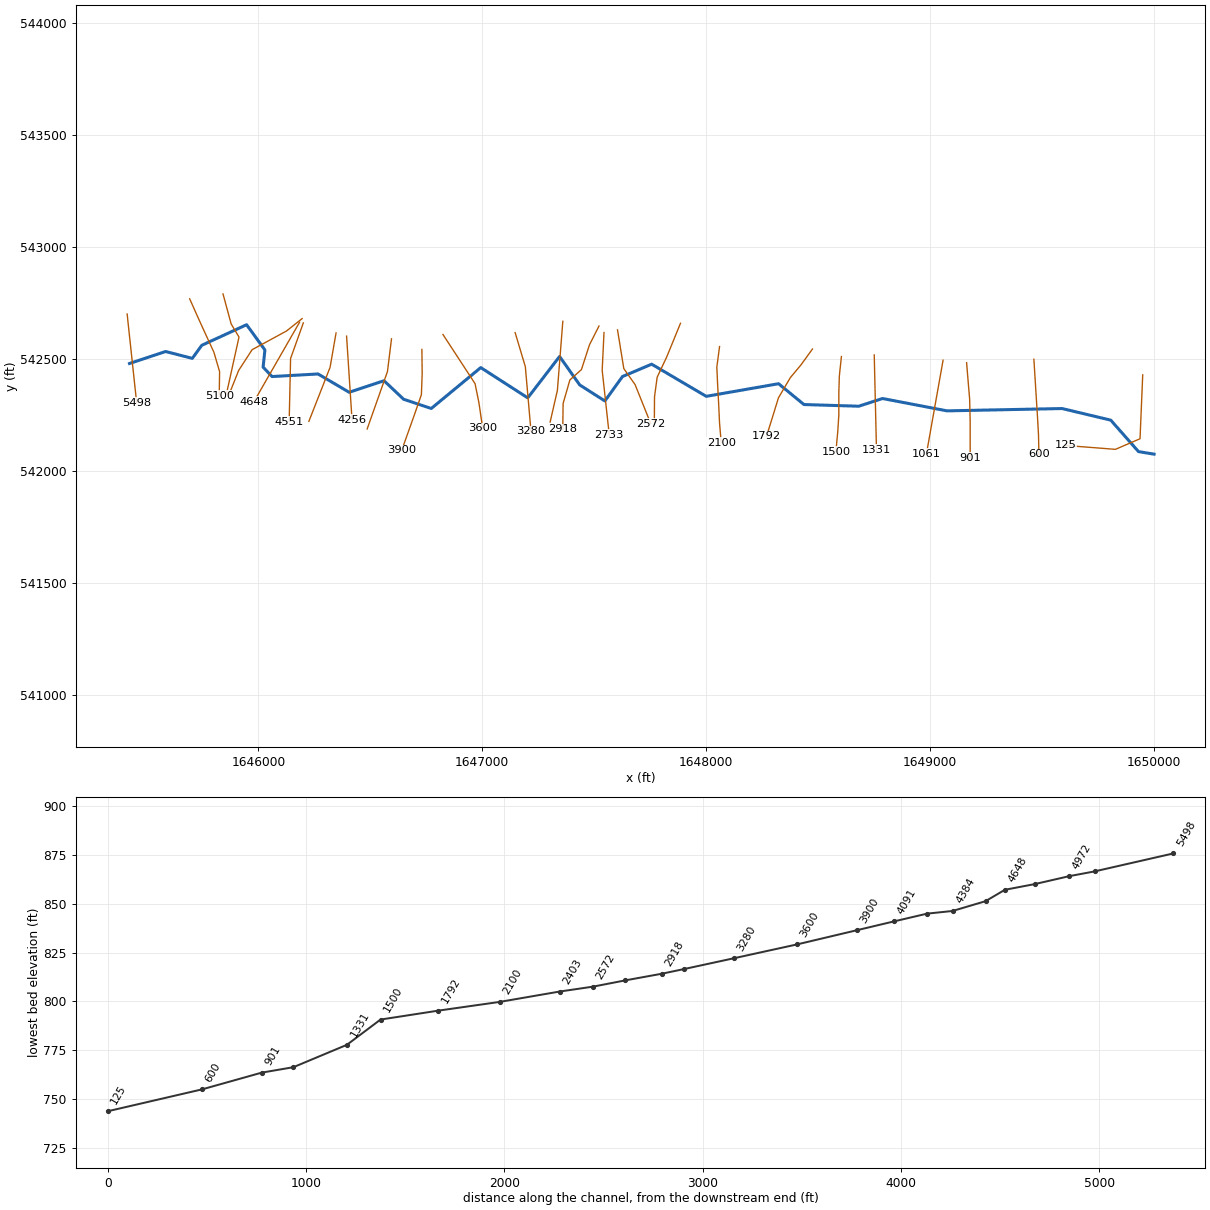
--- HollidaysRn.prj (project) ---

Proj Title=HollidaysRn
Current Plan=p01
Default Exp/Contr=0,0
English Units
Geom File=g01
Flow File=f01
Plan File=p01
BEGIN DESCRIPTION:
---------- MODELED AS PART OF WVEM CTP PROGRAM, 2025----------
Stream Name: Hollidays Run
Flood Zone: AFH
Marshall County, WV
HEC-RAS Version: RAS 6.6
Vertical Datum: NAVD88
Projection: NAD 1983 StatePlane West Virginia N FIPS 4701 (US Feet)
Terrain: 1-meter West Virginia FEMA R3 South Central (collected 2018-2019)
Land Use: 2024 NLCD
Hydrologic Method:
Duda et al., "Estimation of magnitude and frequency of floods for rural, unregulated streams in and near Virginia and West Virginia." September 8, 2025.
Additional Model Notes:
None
END DESCRIPTION:
DSS Export Rating Curves= 0
DSS Export Rating Curve Sorted= 0
DSS Export Volume Flow Curves= 0
DXF OffsetX= 0
DXF OffsetY= 0
DXF ScaleX= 0
DXF ScaleY= 0

--- HollidaysRn.p01 (plan) ---

Plan Title=Floodplain
Program Version=6.60
Short Identifier=Floodplain
Geom File=g01
Flow File=f01
Subcritical Flow
K Sum by GR= 0
Std Step Tol= 0.01
Critical Tol= 0.01
Num of Std Step Trials= 20
Max Error Tol= 0.3
Flow Tol Ratio= 0.001
Split Flow NTrial= 30
Split Flow Tol= 0.02
Split Flow Ratio= 0.02
Log Output Level= 0
Friction Slope Method= 1
Unsteady Friction Slope Method= 2
Unsteady Bridges Friction Slope Method= 1
Parabolic Critical Depth
Global Vel Dist= 0 , 0 , 0
Global Log Level= 0
CheckData=False
Encroach Param=-1 ,0,0, 0
Flow Ratio Tolerance=0.1
Flow Ratio Min Ratio=0.5
Flow Ratio Max Ratio=4
Flow Ratio Max Iterations= 10
Mapping Interval=1HOUR
Computation Time Step Use Courant=        0
Computation Time Step Use Time Series=    0
Computation Time Step Count To Double=0
Computation Time Step Max Doubling=0
Computation Time Step Max Halving=0
Computation Time Step Residence Courant=0
Run HTab= 0
Run UNet= 0
Run Sediment= 0
Run PostProcess= 0
Run WQNet= 0
Run RASMapper=-1
UNET Theta= 0
UNET Theta Warmup= 0
UNET ZTol= 0
UNET ZSATol= 0
UNET MxIter= 0
UNET Max Iter WO Improvement= 0
UNET MaxInSteps= 0
UNET DtIC= 0
UNET DtMin= 0
UNET MaxCRTS= 0
UNET WFStab= 0
UNET SFStab= 0
UNET WFX= 1
UNET SFX= 1
UNET Gravity=32.17405
UNET 1D Methodology=Finite Difference
UNET DSS MLevel= 1
UNET Pardiso=0
UNET DZMax Abort= 0
UNET Use Existing IB Tables= 0
UNET Froude Reduction=False
UNET Froude Limit= 0
UNET Froude Power= 0
UNET D1 Cores= 0
UNET WindReference=Eulerian
UNET WindDragFormulation=Hsu (1988)
UNET D2 Coriolis=0
UNET D2 Cores= 0
UNET D2 Theta= 1
UNET D2 Theta Warmup= 1
UNET D2 Z Tol= 0.01
UNET D2 Volume Tol= 0.01
UNET D2 Max Iterations= 20
UNET D2 Advanced Convergence=0
UNET D2 WS Max Tol=0.15
UNET D2 WS RMS Tol=0.002
UNET D2 WS Stall Tol=1
UNET D2 Equation= 0
UNET D2 RampUpFraction=0.1
UNET D2 TimeSlices= 1
UNET D2 Turbulence Formulation=Non-Conservative (original)
UNET D2 Eddy Viscosity=0.3
UNET D2 Transverse Eddy Viscosity=0.1
UNET D2 Smagorinsky Mixing=0
UNET D2 BCVolumeCheck=0
UNET D2 Cores=0
UNET D2 SolverType=PARDISO (Direct)
UNET D2 Minimum Iterations= 3
UNET D2 Maximum Iterations= 30
UNET D2 Restart Number= 10
UNET D2 Relaxation Coeff=1.3
UNET D2 SOR Precondition Iterations= 10
UNET D2 ILUT Maximum Fill= 8
UNET D2 ILUT Tolerance=1E-08
UNET D2 Convergence Tolerance=0.00001
PS Theta= 1
PS WS Tol= 0.01
PS Volume Tol= 0.01
PS Max Iterations= 20
PS Equation= 0
PS Advance Time Step=-1
PS Target Courant=0.9
PS Time Slices= 1
PS Iterate With 2D=0
PS Project Initial WSE from DS=-1
PS Ramp Up Initial WSE from US=-1
PS Cores=0
UNET D1D2 MaxIter= 0
UNET D1D2 ZTol=0.01
UNET D1D2 QTol=0.1
UNET D1D2 MinQTol=1
Write IC File= 0
Write IC File at Fixed DateTime=0
Write IC File at Sim End=0
Echo Input=False
Echo Parameters=False
Echo Output=False
Write Detailed= 0
HDF Write Warmup=0
HDF Write Time Slices=0
HDF Flush=0
HDF Compression= 1
HDF Chunk Size= 1
HDF Spatial Parts= 1
HDF Use Max Rows=0
HDF Fixed Rows= 1
Calibration Method= 0
Calibration Iterations= 20
Calibration Max Change=0.05
Calibration Tolerance=0.2
Calibration Maximum=1.5
Calibration Minimum=0.5
Calibration Optimization Method= 1
WQ AD Non Conservative
WQ ULTIMATE=-1
WQ Max Comp Step=1HOUR
WQ Output Interval=15MIN
WQ Output Selected Increments= 0
WQ Create Restart=0
WQ Fixed Restart=0
WQ System Summary=0
WQ Write To DSS=0
Sorting and Armoring Iterations= 10
XS Update Threshold= 0.02
Bed Roughness Predictor= 0
Processes Affected by Predictor=Sediment Only
Hydraulics Update Threshold= 0.02
Energy Slope Method= 1
Volume Change Method= 1
Sediment Retention Method= 0
Sediment TS Multiplier= 1
Warm Up Method= 0
XS Weighting Method= 0
Number of US Weighted Cross Sections= 1
Number of DS Weighted Cross Sections= 1
Upstream XS Weight=0
Main XS Weight=1
Downstream XS Weight=0
Number of DS XS's Weighted with US Boundary= 1
Upstream Boundary Weight= 1
Weight of XSs Associated with US Boundary= 0
Number of US XS's Weighted with DS Boundary= 1
Downstream Boundary Weight= 0.5
Weight of XSs Associated with DS Boundary= 0.5
Percentile Method= 0
Sediment Output Level= 3
Mass or Volume Output= 0
Output Increment Type= 1
Profile and TS Output Increment= 1
Transport Output Increment 1
XS Output Flag= 0
XS Output Increment= 10
Read HDF5 Sediment Hotstart= 0
Sediment Hotstart Type= 0
Write Gradation File= 0
Read Gradation Hotstart= 0
Write HDF5 File= 1
Write Binary Output= 1
Write DSS Sediment File= 0
DSS Sediment Output Type= 1
SV Curve= 0
Specific Gage Flag= 0
Subcell Erosion Methods= 0
Subcell Deposition Methods= 0
Advection Scheme= 1
Matrix Solver= 0
Implicit Weighting Factor= 1
Maximum Outer Loop Convergence Iterations= 5
Convergence Maximum Absolute= 0.001
Convergence RMSE= 0.0001
Grain Fractions Max Abs Error= 0.001
Max Subgrid Regions= 1
Max Subgrid Length Scale= 3.402823E+38
Initial Layer Thickness= 3
Min Layer Thickness= 0.1
Max Layer Thickness= 6
Number of Layers= 5

--- HollidaysRn.f01 (steady flow) ---

Flow Title=Flow
Program Version=6.60
Number of Profiles= 1
Profile Names=P100yr
River Rch & RM=HollidaysRn,Main            ,5498
     852
Boundary for River Rch & Prof#=HollidaysRn,Main            , 1
Up Type= 0
Dn Type= 3
Dn Slope=0.02252
DSS Import GetInterval= 0
DSS Import GetPeak= 0
DSS Import FillOption= 0

--- HollidaysRn.g01 (geometry) ---

Geom Title=Geometry
Program Version=6.60

River Reach=HollidaysRn     ,Main
Reach XY= 30
     1645424.497      542480.356     1645585.789      542533.826
     1645705.101      542503.335     1645747.523      542561.665
     1645947.702       542653.58     1646029.454      542540.896
     1646021.499      542464.006      1646061.27      542422.026
     1646266.752      542433.515      1646405.95      542351.764
      1646561.69      542403.355     1646649.379        542320.5
     1646772.724      542279.293      1646993.92      542462.045
     1647203.822      542326.714     1647346.057      542511.758
     1647435.817      542384.713     1647548.363      542312.905
     1647627.076      542421.998     1647757.573      542477.235
     1648001.307      542333.619     1648324.449       542389.99
     1648437.937      542296.955     1648682.601      542289.457
     1648789.098      542323.925     1649077.049      542268.715
     1649591.445      542279.072     1649808.713      542227.202
     1649932.586      542086.644     1650002.158      542075.331

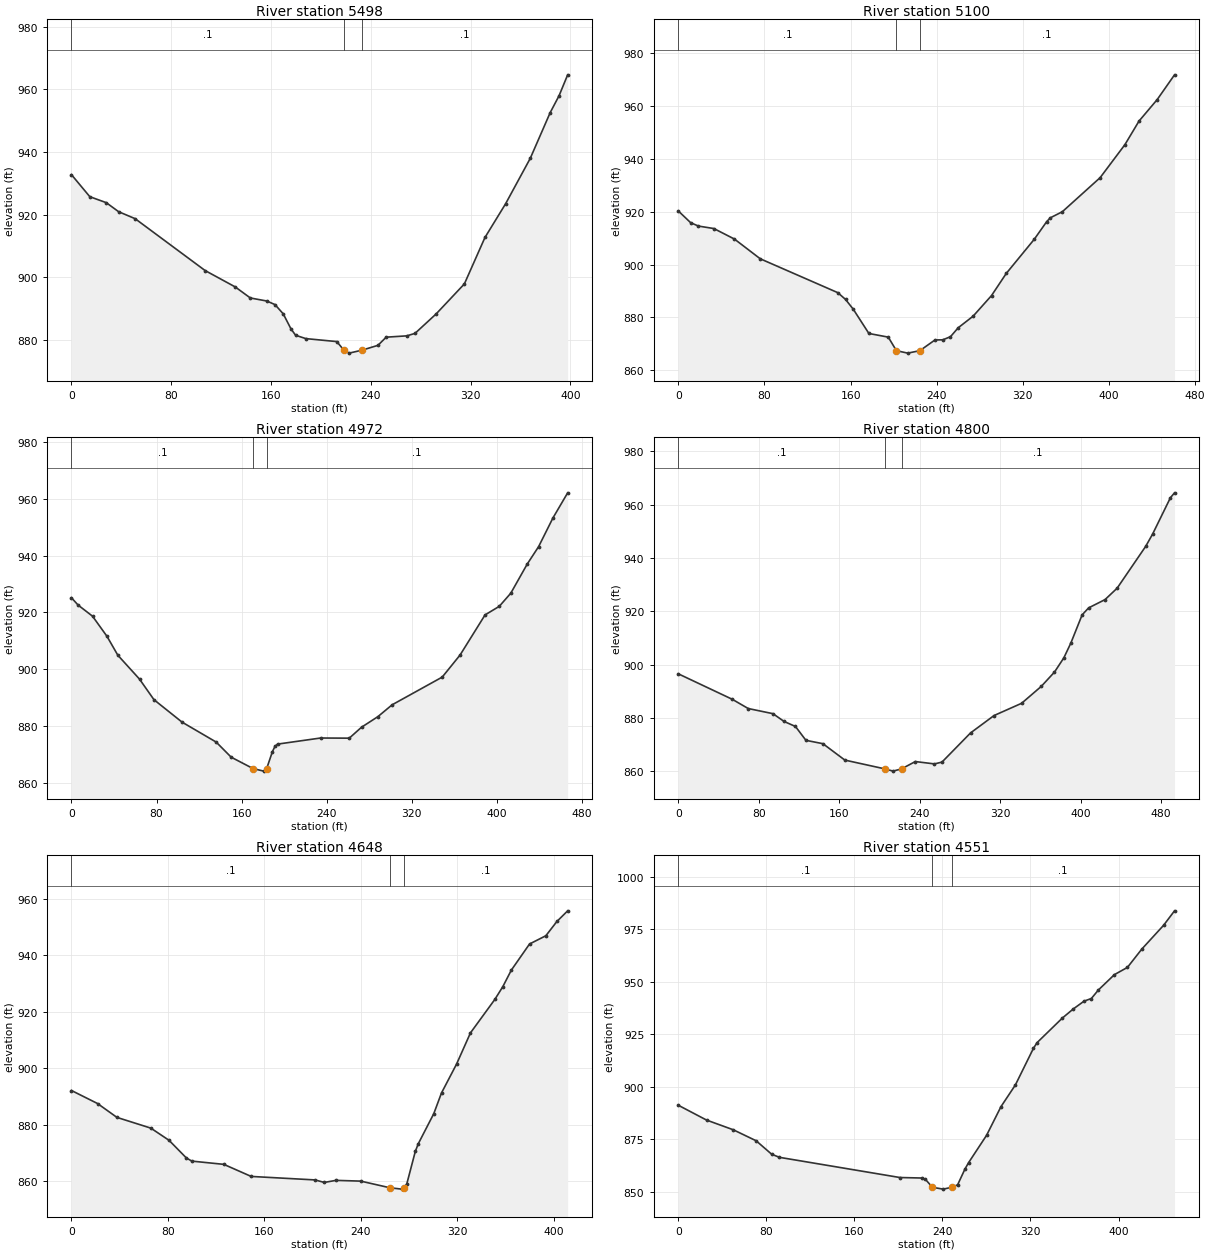
Type RM Length L Ch R = 1 ,5498    ,393,398,398.6
XS GIS Cut Line= 2
1645413.95169674542701.4580133941645456.37238024542305.918417852
#Sta/Elev= 30
       0  932.77    14.7  925.73    27.9  923.82    37.8  920.93      51  918.71
   107.1  902.13   131.3  896.88   143.4  893.35   156.6  892.38   163.2  891.23
   169.8  888.26     176  883.45   179.7  881.43   187.9  880.36   212.7  879.41
   218.4 876.676   222.6  875.72  233.04876.6776   245.7  878.21   252.3  880.82
   268.8  881.24   275.4  882.03   292.3  888.23     315  897.85   331.5   912.7
     348  923.44   367.8  937.98   383.8  952.62   390.9  958.01   397.8  964.69
#Mann= 3 ,-1,0
       0      .1       0   218.4    .045       0  233.04      .1       0
Bank Sta=218.4,233.04
XS Rating Curve= 0 ,0
Exp/Cntr=0.3,0.1

Type RM Length L Ch R = 1 ,5100    ,126.9,127.7,127.8
XS GIS Cut Line= 6
1645693.35743134542769.4439580891645728.91772768542689.487425089
1645759.96556585542621.2152519231645801.77978668542530.376850918
1645827.07009043542443.6230874211645825.36832218542335.601321846
#Sta/Elev= 30
       0  920.33    11.4  915.91    18.6  914.62      33  913.68    52.1   909.7
    76.1  902.22   148.1   889.4   155.3  886.84   162.5  883.12     177  873.94
     195  872.56  202.56867.4262   213.1   866.5  224.31867.4266   238.4  871.49
   245.6  871.53   252.8  872.73     260  876.12   273.8  880.49   290.9  888.29
   304.6  896.68   330.6  909.61   342.2  916.32   345.6  917.76   356.7  920.05
   391.8  932.95   414.8  945.44   427.9  954.37   444.8  962.52   460.9  971.89
#Mann= 3 ,-1,0
       0      .1       0  202.56    .045       0  224.31      .1       0
Bank Sta=202.56,224.31
XS Rating Curve= 0 ,0
Exp/Cntr(USF)=0,0
Exp/Cntr=0.3,0.1

Type RM Length L Ch R = 1 ,4972    ,184.8,172.3,162.2
XS GIS Cut Line= 4
1645842.23023121542791.2495762191645878.79168614542656.797870928
1645913.72636666542598.4348411121645857.78850974542345.185636792
#Sta/Elev= 30
       0  925.17     6.2  922.61    19.8  918.68    33.4  911.58    43.6  904.92
      64   896.5    77.6  889.24     104  881.34   136.1  874.31   150.2  868.99
   170.8  864.97   180.8  864.07   183.6  864.97     189  870.94   191.4  872.79
   193.8  873.59   234.3  875.74   261.3  875.69   272.8  879.54   288.2  883.27
   301.6  887.45   348.7  897.21   365.5  904.99     389  919.13   402.4  922.16
   413.2  926.78   428.7  937.07   439.4  943.21   452.8  953.27   466.7  962.16
#Mann= 3 ,-1,0
       0      .1       0   170.8    .045       0   183.6      .1       0
Bank Sta=170.8,183.6
XS Rating Curve= 0 ,0
Exp/Cntr(USF)=0,0
Exp/Cntr=0.3,0.1

Type RM Length L Ch R = 1 ,4800    ,146.6,151.9,151.3
XS GIS Cut Line= 6
1646195.53392042542680.7692666651646126.00190726542625.540046424
1646060.12277393542589.6943175941645972.25483942542541.952943251
1645912.30778085542449.4111335871645867.98733142542338.495344922
#Sta/Elev= 30
       0  896.53    53.6  886.99    69.5  883.52    94.1  881.59   105.1  878.69
   116.5  876.78   126.9  871.59   143.8  870.33   165.6  864.18  205.26860.8937
   213.6  860.04  222.03860.8928   235.7  863.63   254.7  862.75   262.2  863.42
   290.6  874.36     314  880.89   341.4  885.48   360.9   891.8   374.1  897.19
   383.4  902.52   390.4  908.09   401.6  918.65   408.1  921.28   424.4  924.38
   436.4  928.65   464.8  944.33   471.7  948.95   489.4  962.58   493.5  964.42
#Mann= 3 ,-1,0
       0      .1       0  205.26    .045       0  222.03      .1       0
Bank Sta=205.26,222.03
XS Rating Curve= 0 ,0
Exp/Cntr(USF)=0,0
Exp/Cntr=0.3,0.1

Type RM Length L Ch R = 1 ,4648    ,93.1,97.5,98.2
XS GIS Cut Line= 2
1646184.57249948542665.1349858971645979.72682837542308.403744016
#Sta/Elev= 30
       0  892.05    21.6  887.44    37.7  882.52    65.8  878.72    80.9   874.4
    95.3  868.13    99.8  867.03   126.3  865.88     149   861.6     202  860.36
   209.6  859.47   219.2   860.2   239.8  859.94  264.16  857.57   273.9   857.1
   275.6  857.57     278  858.91   285.1   870.5   287.6  873.23   300.4  883.85
   306.8  891.19   319.3  901.43   330.8  912.47     351  924.32   357.6  928.83
   364.7  934.72   379.8  943.98   393.3  946.89   402.5  951.97   411.4  955.73
#Mann= 3 ,-1,0
       0      .1       0  264.16    .045       0   275.6      .1       0
Bank Sta=264.16,275.6
XS Rating Curve= 0 ,0
Exp/Cntr(USF)=0,0
Exp/Cntr=0.3,0.1

Type RM Length L Ch R = 1 ,4551    ,168.7,166.5,162.8
XS GIS Cut Line= 3
1646201.17007281542661.7032044241646144.22271278542502.826871299
1646137.91242039542220.787324672
#Sta/Elev= 30
       0  891.21    25.6  884.17      50  879.52    70.7   874.3    84.8   867.9
    91.8  866.42   201.3   856.8     221  856.56   224.3  856.06  230.89852.1367
   240.7  851.27  248.46852.1346   253.8  853.33   260.4  860.78   263.7  863.83
   280.1   876.9   293.2  890.56   306.3   900.9   322.7  918.34     326  921.04
     349  932.76   358.8  937.04   368.7   940.8   375.3  942.05   381.8  946.16
   396.3  953.43   408.1  956.87   421.2  965.61   440.9  976.88   450.9  983.81
#Mann= 3 ,-1,0
       0      .1       0  230.89    .045       0  248.46      .1       0
Bank Sta=230.89,248.46
XS Rating Curve= 0 ,0
Exp/Cntr(USF)=0,0
Exp/Cntr=0.3,0.1

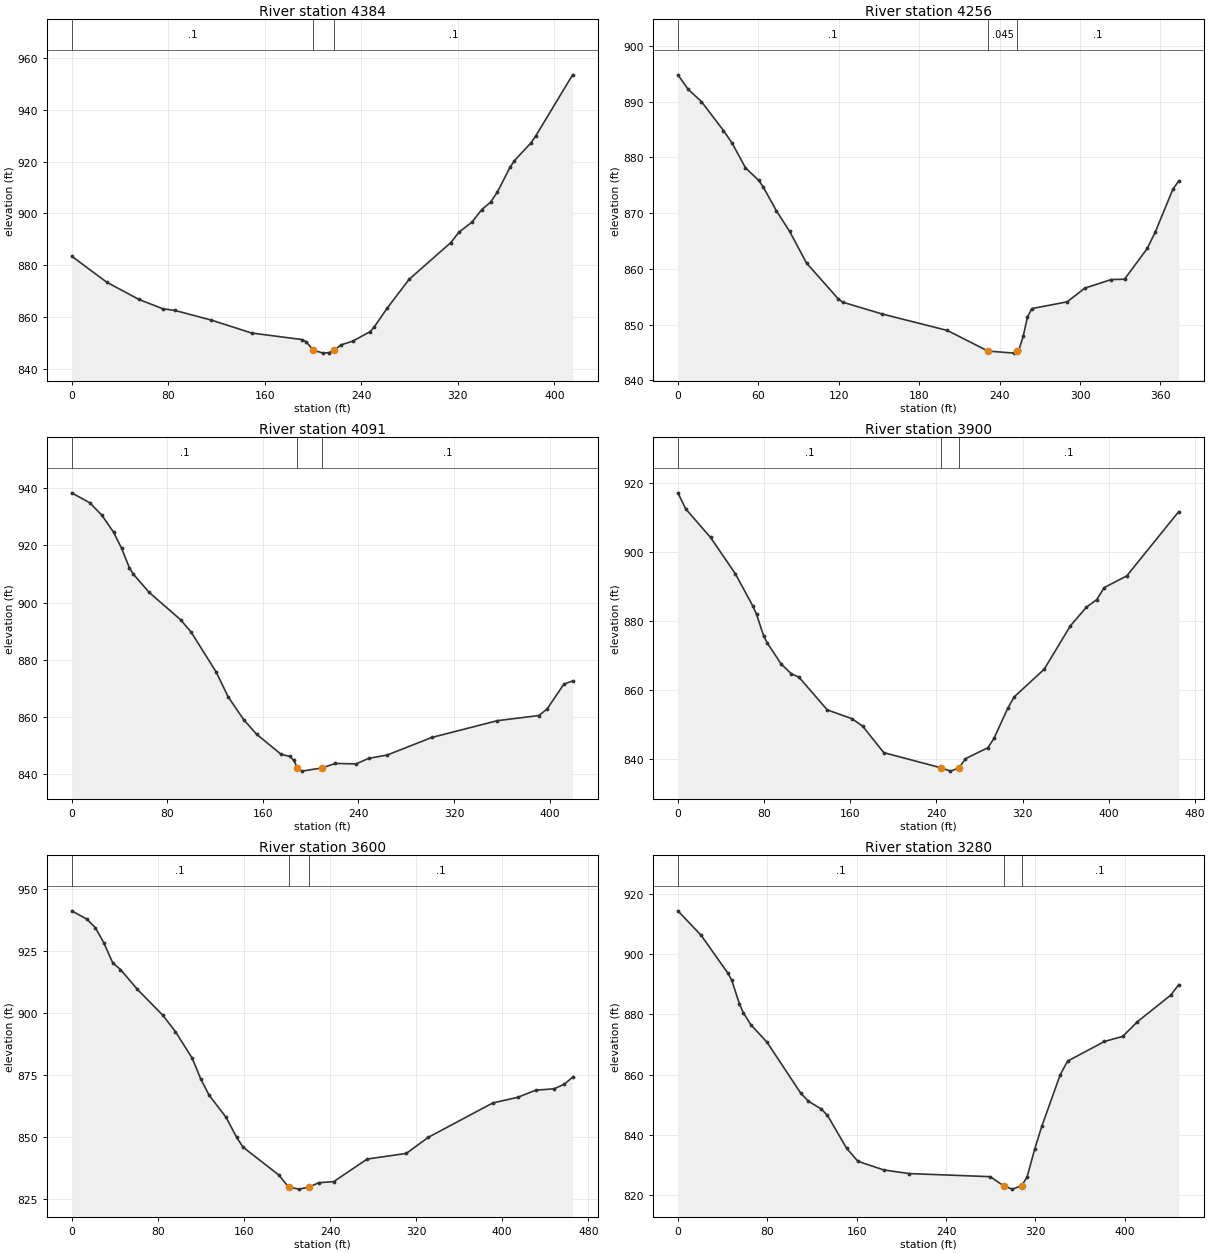
Type RM Length L Ch R = 1 ,4384    ,117.2,127.8,127.3
XS GIS Cut Line= 3
1646347.37965616542616.9508912851646320.66977914542463.166750878
1646225.97112426542221.968467503
#Sta/Elev= 30
       0  883.55      29  873.56    55.6  866.94    75.5  863.32    85.6  862.68
   115.6  858.98   149.2  853.98   190.7  851.49   194.3  850.66   200.3847.3933
   208.4  846.25   213.3  846.44  217.48847.3942   223.4  849.45     233  850.87
   247.1  854.45   250.7  856.27   261.3  863.44   279.6  874.62   314.1  888.74
   321.1  892.84   331.7  896.63   339.8  901.43   347.4  904.46   352.9  908.32
   363.4  917.82     367  920.33   380.3  926.99   384.6  929.81   415.2  953.36
#Mann= 3 ,-1,0
       0      .1       0   200.3    .045       0  217.48      .1       0
Bank Sta=200.3,217.48
XS Rating Curve= 0 ,0
Exp/Cntr(USF)=0,0
Exp/Cntr=0.3,0.1

Type RM Length L Ch R = 1 ,4256    ,161.3,164.9,153
XS GIS Cut Line= 2
1646394.37457295542602.6299808161646418.66539338 542229.69350667
#Sta/Elev= 30
       0  894.82     7.7  892.21    17.6  890.01      34  884.83    40.6  882.51
    50.4  878.15    60.3  875.88    63.6  874.74    73.4  870.46    83.3  866.76
      96  861.05   119.5  854.67   122.8  854.05   152.4  851.92     201  848.97
   231.3  845.27     251   844.9  253.18  845.23   254.3  845.41   257.6  847.91
   260.8   851.4   264.1  852.89   290.4   854.1   303.6  856.56   323.3   858.1
   333.2  858.16   350.2  863.69   356.2  866.65   369.3  874.31   373.7   875.8
#Mann= 3 ,0,0
       0      .1       0   231.3    .045       0  253.18      .1       0
Bank Sta=231.3,253.18
XS Rating Curve= 0 ,0
Exp/Cntr(USF)=0,0
Exp/Cntr=0.3,0.1

Type RM Length L Ch R = 1 ,4091    ,188.4,191,186.4
XS GIS Cut Line= 3
1646595.08593536542590.3911356111646577.02065669542444.436651967
1646486.36895287542187.859954551
#Sta/Elev= 30
       0  938.44    15.2  934.93    25.2  930.62    35.1  924.61    41.7  919.05
    48.3  912.18    51.6  909.94    64.8  903.58    91.3  893.93   100.1  889.57
     121  875.62   130.9  867.03   144.2  858.85   154.8  853.88   175.3  846.85
   182.3  846.16   185.8  844.84  188.81 842.135   192.7  840.98  209.79842.1313
   220.6  843.67     238  843.52   248.4  845.43   264.2  846.64   301.4  852.78
   356.3  858.65   391.1  860.46     398  862.83   411.9  871.47   419.2  872.55
#Mann= 3 ,-1,0
       0      .1       0  188.81    .045       0  209.79      .1       0
Bank Sta=188.81,209.79
XS Rating Curve= 0 ,0
Exp/Cntr(USF)=0,0
Exp/Cntr=0.3,0.1

Type RM Length L Ch R = 1 ,3900    ,292.2,300.4,307.3
XS GIS Cut Line= 6
1646730.89407018542543.2387018351646732.14472385542432.609658003
1646728.61257868542340.9120067511646695.75864175542246.459111676
1646670.53329851542175.8286755091646641.10356735542093.426281258
#Sta/Elev= 30
       0  917.26     7.3  912.57    30.3  904.29    53.3  893.75    69.7  884.27
      73  881.95    79.5  875.75    82.8   873.7    95.9  867.47   105.2  864.68
   112.3  863.69   138.6  854.18   161.6   851.6   171.4  849.47   191.1  841.74
  244.41837.3231     253  836.37     261837.3232   266.9  839.98   287.7  843.18
   293.3  845.86   306.1  854.61   312.1  857.94     340     866   364.3  878.61
   379.1  884.01   388.7   886.2   395.7  889.72   416.6  893.12   464.9  911.83
#Mann= 3 ,-1,0
       0      .1       0  244.41    .045       0     261      .1       0
Bank Sta=244.41,261
XS Rating Curve= 0 ,0
Exp/Cntr(USF)=0,0
Exp/Cntr=0.3,0.1

Type RM Length L Ch R = 1 ,3600    ,326.4,319.5,315
XS GIS Cut Line= 6
1646824.95556185542609.9846313451646872.78584675542536.714764759
 1646913.7847805542473.9127250021646968.45035359 542390.17700009
1646985.76035833542304.6040085111647002.56839558542190.201350167
#Sta/Elev= 30
       0  941.16      14  937.82    21.9  934.43    29.7  928.41    38.2  920.15
    45.3  917.54      61  909.57    84.6  899.15    96.3  892.58     112  881.82
   119.8  873.59   127.7   866.9   143.3  858.14   153.2  850.02   159.2  846.03
   192.3  834.87  201.55  829.96   211.2  829.14  220.62829.9623   229.5  831.73
   243.3  832.13   274.5  841.24   310.9  843.52   331.4  850.02   391.3  863.84
   414.5  866.11     431  868.95   448.2  869.53   457.6  871.37   465.4  874.18
#Mann= 3 ,-1,0
       0      .1       0  201.55    .045       0  220.62      .1       0
Bank Sta=201.55,220.62
XS Rating Curve= 0 ,0
Exp/Cntr(USF)=0,0
Exp/Cntr=0.3,0.1

Type RM Length L Ch R = 1 ,3280    ,253.3,249.5,247
XS GIS Cut Line= 3
1647147.51528418542618.1552186761647193.02004522542466.262106771
1647218.34358861542177.542824291
#Sta/Elev= 30
       0  914.37    20.8  906.25    44.8  893.67    48.2  891.34      55  883.59
    58.5  880.62    65.3  876.56    79.8  870.77   109.8  853.96   116.7  851.22
   128.2  848.65   133.8  846.56     151  835.62   161.1  831.27   184.2   828.4
   207.2  827.19   279.7  826.16   291.5 823.127   299.4  822.03  307.62823.1257
   312.6  826.06   319.4  835.31   325.8  842.92   342.2  859.95   348.8  864.49
   381.8  871.02   398.2  872.71   411.4  877.59   441.1  886.37   448.4  889.89
#Mann= 3 ,-1,0
       0      .1       0   291.5    .045       0  307.62      .1       0
Bank Sta=291.5,307.62
XS Rating Curve= 0 ,0
Exp/Cntr(USF)=0,0
Exp/Cntr=0.3,0.1

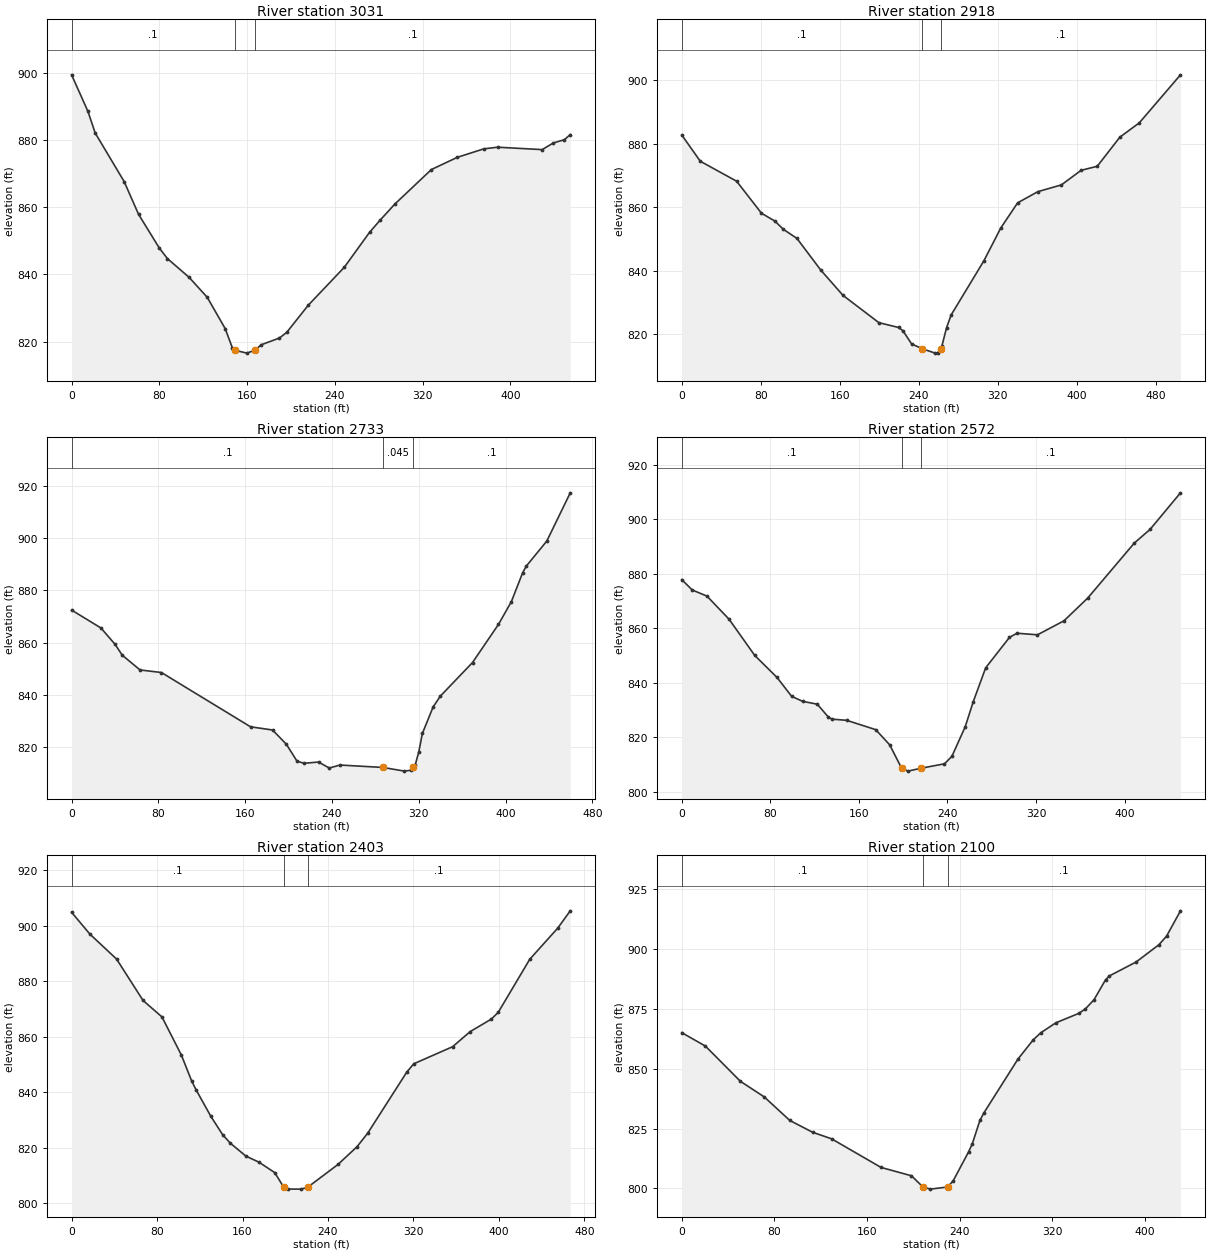
Type RM Length L Ch R = 1 ,3031    ,119.4,113.5,105.6
XS GIS Cut Line= 3
1647360.57699903542668.9119787121647336.29529265542360.534307685
1647303.91968415542218.891020468
#Sta/Elev= 30
       0  899.37    14.9  888.48    21.5  882.06    47.9  867.61      61  857.88
    80.1  847.74    87.4  844.67   107.1   839.1   123.6  833.18     140  823.85
   146.6  818.07  148.85817.3997   159.8  816.54  167.06817.4013   172.9  819.03
   189.4  821.02   196.1  822.71   215.7  830.78   248.6  842.09   271.6  852.48
   281.5   856.2   294.7  860.91     328  871.18   351.6  874.81   375.7  877.33
   388.4  877.83     429  877.11   439.1  879.08   449.2  880.06   454.6  881.58
#Mann= 3 ,-1,0
       0      .1       0  148.85    .045       0  167.06      .1       0
Bank Sta=148.85,167.06
XS Rating Curve= 0 ,0
Exp/Cntr(USF)=0,0
Exp/Cntr=0.3,0.1

Type RM Length L Ch R = 1 ,2918    ,167.2,184,191.5
XS GIS Cut Line= 6
1647522.16118842542647.7683484261647479.52118184542563.616941929
 1647443.6693177 542453.100300691647392.12632608542406.866299697
1647361.79208659542301.7778986691647360.29897934542185.794206753
#Sta/Elev= 30
       0  882.72    18.7  874.49    55.5  868.21    80.7  858.13    94.3  855.66
   102.8  853.08   116.6  850.22   140.7  840.27   163.2  832.31   199.6   823.7
   219.6  822.19     224  821.14   232.8     817  243.78815.4772   256.6  814.12
   259.2  814.21  262.06815.4773   263.5  816.43   268.2  822.16   272.8  826.13
     306  843.19     323  853.45   340.1  861.39   360.6  864.92   384.5  867.05
   404.4  871.63   420.8  872.91   443.7  882.07   463.4  886.57   505.1  901.68
#Mann= 3 ,-1,0
       0      .1       0  243.78    .045       0  262.06      .1       0
Bank Sta=243.78,262.06
XS Rating Curve= 0 ,0
Exp/Cntr(USF)=0,0
Exp/Cntr=0.3,0.1

Type RM Length L Ch R = 1 ,2733    ,147.2,161.9,164.4
XS GIS Cut Line= 3
1647544.50916253542618.6228999841647536.43015108542449.812641117
1647568.09077439542160.915612875
#Sta/Elev= 30
       0  872.44      27  865.59    40.1  859.29    46.7  855.14    63.1  849.49
    82.8  848.51   164.9  827.71   185.2  826.48   197.9  821.05   207.8   814.5
   214.4  813.73   227.6   814.2   237.5  811.91   247.4  813.05     287  812.13
   306.8  810.72   313.1   811.1  315.05 812.121   316.7  813.08     320   818.1
   323.3  825.15   333.2  835.31   339.8  839.44   369.5  852.33   393.4  866.93
   405.3  875.65   415.7  886.71     419  889.25     438   898.9   459.6  917.37
#Mann= 3 ,-1,0
       0      .1       0     287    .045       0  315.05      .1       0
Bank Sta=287,315.05
XS Rating Curve= 0 ,0
Exp/Cntr(USF)=0,0
Exp/Cntr=0.3,0.1

Type RM Length L Ch R = 1 ,2572    ,179.8,168.9,157.5
XS GIS Cut Line= 4
1647604.91669347542630.5230117271647632.95512513542457.566537806
1647683.43476089542385.9831347671647753.34686751542211.778823179
#Sta/Elev= 30
       0   877.8     9.4  874.01    22.7  871.77    42.7  863.27    65.9  849.98
    85.9  841.96    99.2  834.99   109.2  833.13   122.4   832.1   132.4  827.35
   135.7  826.61     149  826.17   175.2  822.75   187.8  817.17  198.54808.6191
   204.3  807.53  216.42808.6187   237.3  810.22     244  812.96     256  823.79
   263.2  832.92   274.5  845.44     296  856.62   302.8  858.14   321.3  857.56
   345.2  862.69   366.7  871.05   408.8  891.24     423  896.24   450.5  909.67
#Mann= 3 ,-1,0
       0      .1       0  198.54    .045       0  216.42      .1       0
Bank Sta=198.54,216.42
XS Rating Curve= 0 ,0
Exp/Cntr(USF)=0,0
Exp/Cntr=0.3,0.1

Type RM Length L Ch R = 1 ,2403    ,296.4,302.2,307
XS GIS Cut Line= 6
1647886.32187742542660.1538223331647853.19136626542579.168420002
1647824.79378526542509.752548337 1647782.1258916542419.163490668
1647770.21154533542331.8126154991647769.42775425542215.844671592
#Sta/Elev= 30
       0   904.9    17.1  897.03    42.1  888.02    66.9  873.07    84.6  867.14
   102.8  853.35   112.4  844.02   116.5  840.86   130.4  831.24   141.3  824.71
   148.4  821.65   163.1  816.94   175.4  814.73   190.2  810.96  198.55805.7031
   202.5  805.03   214.9  805.01  221.05805.7029   249.4  813.92   267.3  820.36
   277.3  825.26   313.7  847.19   320.3  850.23   356.7   856.4   373.1  861.84
   392.8  866.33   399.3  868.74   428.9  887.95   455.1  899.19   466.8  905.42
#Mann= 3 ,-1,0
       0      .1       0  198.55    .045       0  221.05      .1       0
Bank Sta=198.55,221.05
XS Rating Curve= 0 ,0
Exp/Cntr(USF)=0,0
Exp/Cntr=0.3,0.1

Type RM Length L Ch R = 1 ,2100    ,310.7,308.7,298.9
XS GIS Cut Line= 6
1648060.81234209542556.1071144191648048.58631667542464.036760509
1648052.02167726542388.9571862521648057.27133867542289.092556596
1648060.76542617542214.1737431731648068.21062125542126.940649927
#Sta/Elev= 30
       0  865.05    20.4  859.44    50.6  844.73    71.1  838.25    93.2  828.41
   112.9  823.46   129.3  820.73     172  808.78   198.3  805.28  208.18800.6205
   214.7  799.71  229.68 800.621   234.4  803.26   247.6  815.25   250.9  818.74
   257.4  828.41   260.8  831.52   290.3  854.05   303.4  862.05     310  865.02
   323.1   869.2   342.8  873.11   348.5  874.98     356  878.85   365.9  887.15
   369.2  888.76   392.2  894.54     412  901.79   418.6  905.38   430.6  915.94
#Mann= 3 ,-1,0
       0      .1       0  208.18    .045       0  229.68      .1       0
Bank Sta=208.18,229.68
XS Rating Curve= 0 ,0
Exp/Cntr(USF)=0,0
Exp/Cntr=0.3,0.1

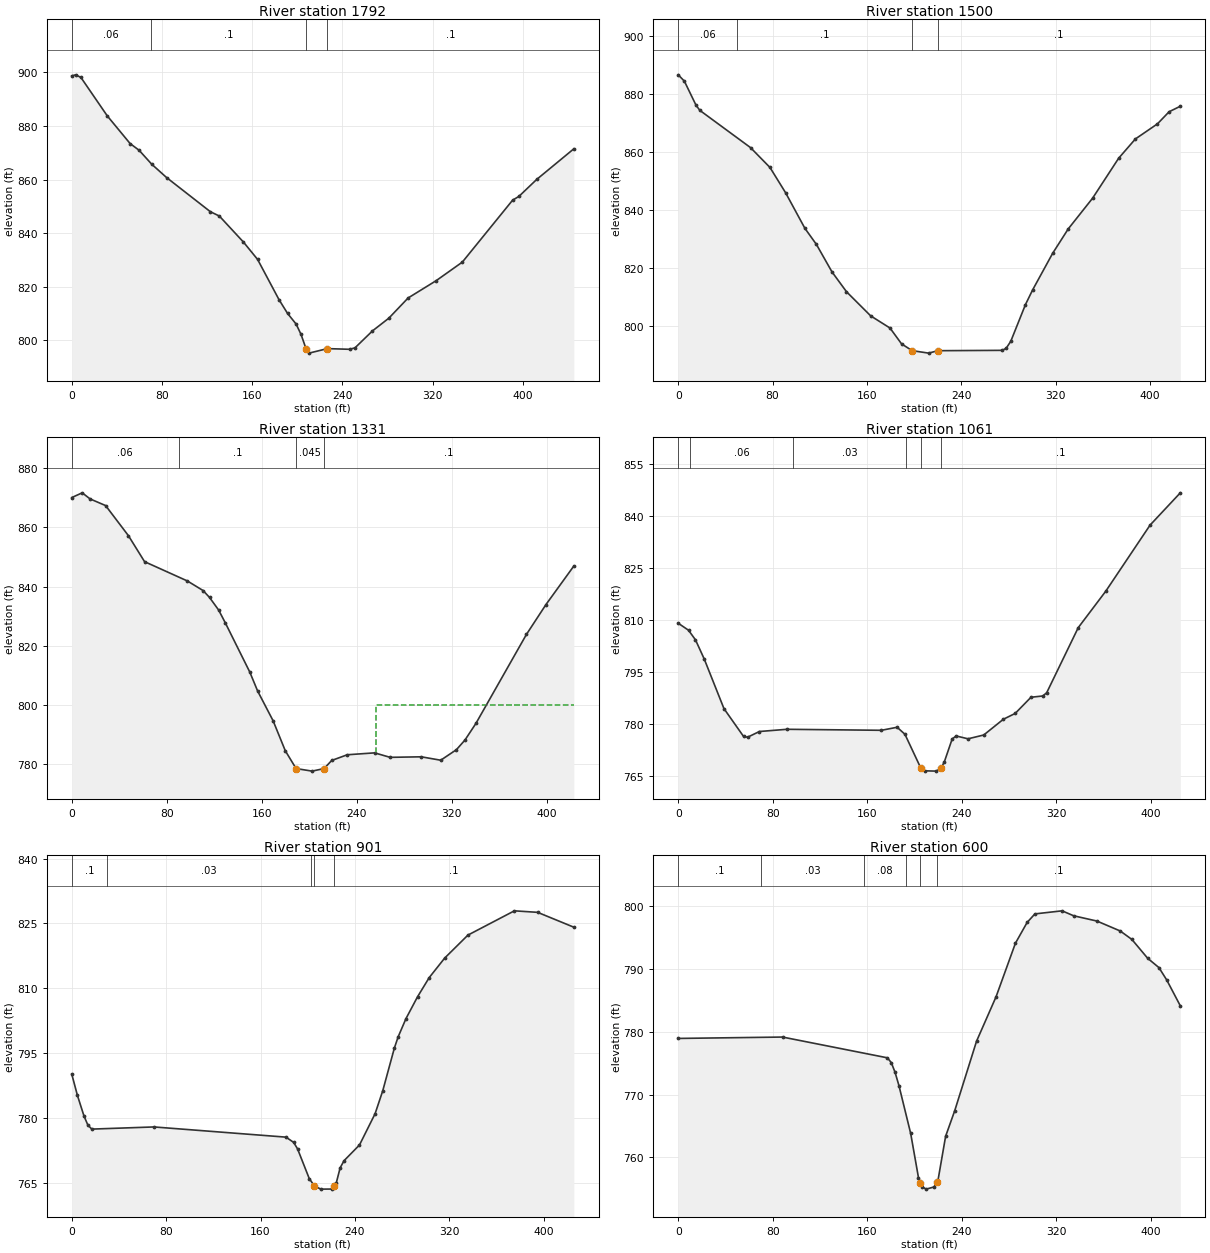
Type RM Length L Ch R = 1 ,1792    ,279.6,291.6,289.1
XS GIS Cut Line= 6
1648475.83382176  542545.00510251648424.49993493542473.978997841
1648376.46820684542416.4016851781648323.79869276542326.580670595
1648299.33089392542247.0480212571648270.92511085542156.009817511
#Sta/Elev= 30
       0  898.66     3.4  899.06     8.1  898.09    31.5  883.74    51.7  873.44
    59.8  870.89    70.9  865.72    84.1  860.74   122.9  848.01   130.9  846.38
   152.3  836.66   164.8  830.21   183.8   815.2   191.4  810.05     199  806.08
   203.3  802.27  207.74796.9362   210.4  795.25  226.71796.9338   246.4  796.68
   251.2  797.22   266.7  803.54   281.2  808.28   298.3  815.82   323.2  822.28
   346.4   829.2     391  852.31   396.6  853.72   412.3  860.02   445.3  871.47
#Mann= 4 ,-1,0
       0     .06       0      70      .1       0  207.74    .045       0
  226.71      .1       0
Bank Sta=207.74,226.71
XS Rating Curve= 0 ,0
Exp/Cntr(USF)=0,0
Exp/Cntr=0.3,0.1

Type RM Length L Ch R = 1 ,1500    ,168.5,169.4,169
XS GIS Cut Line= 6
  1648605.240059542511.5711142571648595.98843709542424.219254836
1648593.65707693542349.2194048321648593.65707693542249.219276756
 1648588.7660106542174.2318939271648580.63020009542086.813105509
#Sta/Elev= 30
       0  886.63     5.2  884.45    15.1  876.14    18.4  874.35    61.3  861.54
    77.8  854.69      91  846.01   107.4  833.72   117.2  828.15   130.4  818.68
   142.7  811.85   163.2  803.53   179.6  799.33   189.4  793.87  198.39791.5309
   212.4  790.68  220.13791.5175   274.8  791.64   278.1  792.35     282  794.74
   294.5  807.44   300.5  812.44   317.5  825.07   330.7  833.48   351.4  844.09
   373.5  857.87   387.7  864.52   406.4  869.72   416.3   873.9   425.8   875.8
#Mann= 4 ,-1,0
       0     .06       0      50      .1       0  198.39    .045       0
  220.13      .1       0
Bank Sta=198.39,220.13
XS Rating Curve= 0 ,0
Exp/Cntr(USF)=0,0
Exp/Cntr=0.3,0.1

Type RM Length L Ch R = 1 ,1331    ,272.1,270,268.1
XS GIS Cut Line= 2
1648751.90754965542518.4759405731648761.90002141542095.794385069
#Sta/Elev= 30
       0  870.05     8.8  871.64    15.4  869.59    28.5  867.34    47.7  857.19
    61.3  848.42    97.4   841.9   110.6  838.67     116  836.35   123.7  832.09
   129.4   827.7   149.9  811.19   156.5   804.8   169.6   794.7   179.8  784.64
   188.9 778.624   202.4  777.76  212.46778.6254   218.9  781.36     232  783.28
     255  783.92   268.1  782.41   294.3  782.59   310.7  781.44   323.9  784.99
   331.1  788.24   340.3  793.83   382.9  823.89   399.3  833.94   422.8  846.95
#Mann= 4 ,-1,0
       0     .06       0      90      .1       0   188.9    .045       0
  212.46      .1       0
#XS Ineff= 2 , 0
                          256.08           800.2
Permanent Ineff=
       F       F
Bank Sta=188.9,212.46
XS Rating Curve= 0 ,0
Exp/Cntr(USF)=0,0
Exp/Cntr=0.3,0.1

Type RM Length L Ch R = 1 ,1061    ,157.3,159.4,160.7
XS GIS Cut Line= 6
1649059.49413239542495.2296308021649044.18970106542409.078228313
1649031.07194514542335.2342158891649013.58116649542236.775751386
1649000.46341057542162.9320670551648985.15897923542076.780664552
#Sta/Elev= 30
       0  809.04     8.7  807.02    14.6  804.24      22  798.71    38.7  784.37
    55.3  776.32    58.7   776.1    68.7  777.75      92  778.39     172   778.1
   185.3  778.98   191.9  776.95  205.17767.2906   208.6  766.39   218.6   766.3
  222.69767.2958   225.3  769.03   231.9  775.61   235.3  776.46   245.3  775.64
   258.6  776.74   275.2  781.29   285.2  782.97   298.6  787.65   308.6  788.02
   311.9  788.96   338.6  807.77   361.9   818.3   399.4   837.4     425  846.73
#Mann= 6 ,-1,0
       0      .1       0      10     .06       0    97.5     .03       0
   192.5      .1       0  205.17    .045       0  222.69      .1       0
Bank Sta=205.17,222.69
XS Rating Curve= 0 ,0
Exp/Cntr(USF)=0,0
Exp/Cntr=0.3,0.1

Type RM Length L Ch R = 1 ,901     ,300.6,301.2,301.2
XS GIS Cut Line= 6
1649164.62771976542483.9770093411649171.75336167 542396.47718434
1649178.13425443542321.4773343351649180.48497151 542221.47720626
1649180.48497151542146.4770281761649180.48497151542058.977203175
#Sta/Elev= 30
       0  790.12     4.8   785.2    10.4  780.41    13.7  778.31      17  777.41
    69.7  777.91   181.6  775.55   188.1  774.33   191.4  772.83   201.3  765.97
  205.63764.2709   211.1  763.52     221  763.54  222.67764.2714   224.2  764.94
   227.5  768.45   230.8   770.1   243.9  773.74   257.1  780.96   263.6  786.27
   273.5   796.2   276.7  798.78   283.3  802.98   293.1  808.03     303  812.47
   316.1  816.98   335.8   822.3   375.2  827.92   394.9  827.57   425.6  824.13
#Mann= 5 ,-1,0
       0      .1       0      30     .03       0  203.06      .1       0
  205.63    .045       0  222.67      .1       0
Bank Sta=205.63,222.67
XS Rating Curve= 0 ,0
Exp/Cntr(USF)=0,0
Exp/Cntr=0.3,0.1

Type RM Length L Ch R = 1 ,600     ,484.3,475.2,462.1
XS GIS Cut Line= 6
1649465.16944151542499.3713355061649470.62677968542412.041457668
1649475.30524801542337.1876047551649481.54211217542237.382358179
1649485.76716934542162.4999620021649487.71828093542074.951252595
#Sta/Elev= 30
       0  778.97    88.3  779.19   177.1  775.88   180.4  775.11   183.6  773.56
   186.9  771.43   196.8  763.83   203.4  756.79  205.11756.0054   206.7  755.31
   209.9  754.95   216.5  755.29  219.07756.0065   219.8  756.21   226.4  763.38
   234.1  767.45   252.6  778.54   269.1  785.61   285.5  794.15   295.4  797.46
     302  798.82     325  799.31   334.8  798.52   354.5  797.68   374.2   796.1
   384.1  794.75   397.5  791.74     407  790.26   413.6  788.29   425.1  784.17
#Mann= 6 ,-1,0
       0      .1       0      70     .03       0   157.5     .08       0
   192.5      .1       0  205.11    .045       0  219.07      .1       0
Bank Sta=205.11,219.07
XS Rating Curve= 0 ,0
Exp/Cntr(USF)=0,0
Exp/Cntr=0.3,0.1

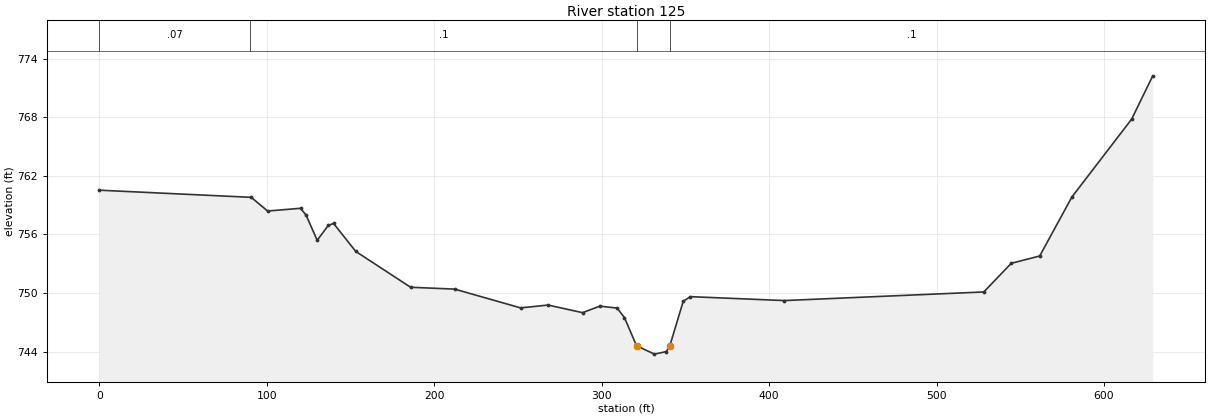
Type RM Length L Ch R = 1 ,125     ,,,
XS GIS Cut Line= 4
1649951.44668333 542429.664289961649939.45444396542144.048679427
1649829.37579473542096.7636548291649606.65542266542114.193843561
#Sta/Elev= 30
       0  760.53    90.7   759.8   100.5   758.4   120.2  758.68   123.5  757.97
   130.1  755.41   136.7  756.92   139.9  757.13   153.1  754.27   185.9   750.6
   212.2  750.41   251.6  748.49     268  748.78   288.6     748   298.9  748.67
   309.2  748.47   313.6   747.5320.8123744.6174   331.5  743.76   338.6  744.02
340.6722744.5984   348.7  749.16   352.9  749.64     409  749.24   528.2  750.12
   544.6  753.05   561.6   753.8   580.8  759.83   616.5   767.8   629.1  772.23
#Mann= 4 ,-1,0
       0     .07       0      90      .1       0320.8123    .045       0
340.6722      .1       0
Bank Sta=320.8123,340.6722
XS Rating Curve= 0 ,0
Exp/Cntr(USF)=0,0
Exp/Cntr=0.3,0.1
LCMann Table=0

Chan Stop Cuts=-1
Use User Specified Reach Order=0
Composite Channel Slope=5